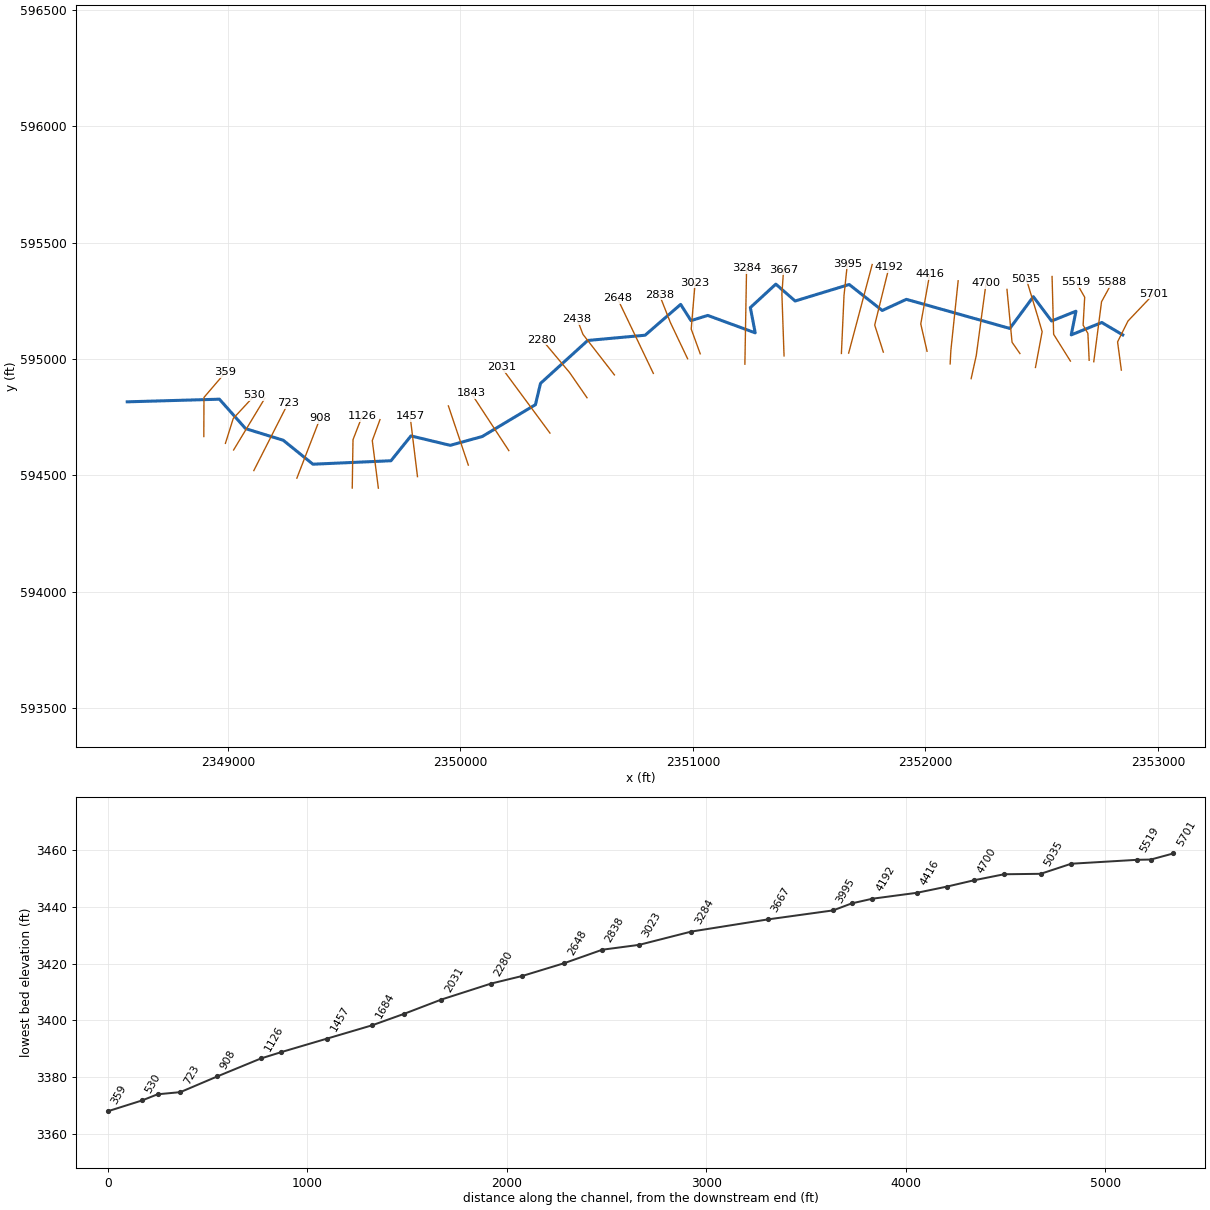
--- BRNGRN.prj (project) ---

Proj Title=BRNGRN
Current Plan=p01
Default Exp/Contr=0,0
English Units
Geom File=g01
Flow File=f01
Plan File=p01
Background Map Layer=Inundation Boundary (01pct Value_0)
BEGIN DESCRIPTION:
----------MODEL BY WOOD PLC 2021----------
Stream Name: Burning Run
Flood Zone: Enhanced Approximate
Pocahontas County, WV
HEC-RAS Version: RAS 6.1
Vertical Datum: NAVD88
Projection: NAD 1983 StatePlane West Virginia S FIPS 4702 (US Feet)
Terrain: 1-meter LIDAR (FEMA Region III 3DEP collected 2016-2018)
Land Use: 2019 NLCD
Hydrologic Method:
WV SIR2010-5033 regression equations
Model Notes:
END DESCRIPTION:
DSS Export Rating Curves= 0
DSS Export Rating Curve Sorted= 0
DSS Export Volume Flow Curves= 0
DXF OffsetX= 0
DXF OffsetY= 0
DXF ScaleX= 0
DXF ScaleY= 0

--- BRNGRN.p01 (plan) ---

Plan Title=Floodplain
Program Version=6.10
Short Identifier=Floodplain
Geom File=g01
Flow File=f01
Subcritical Flow
K Sum by GR= 0
Std Step Tol= 0.01
Critical Tol= 0.01
Num of Std Step Trials= 20
Max Error Tol= 0.3
Flow Tol Ratio= 0.001
Split Flow NTrial= 30
Split Flow Tol= 0.02
Split Flow Ratio= 0.02
Log Output Level= 0
Friction Slope Method= 1
Unsteady Friction Slope Method= 2
Unsteady Bridges Friction Slope Method= 1
Parabolic Critical Depth
Global Vel Dist= 0 , 0 , 0
Global Log Level= 0
CheckData=True
Encroach Param=-1 ,0,0, 0
Mapping Interval=1HOUR
Computation Time Step Use Courant=        0
Computation Time Step Use Time Series=    0
Computation Time Step Count To Double=0
Computation Time Step Max Doubling=0
Computation Time Step Max Halving=0
Computation Time Step Residence Courant=0
Run HTab= 0
Run UNet= 0
Run Sediment= 0
Run PostProcess= 0
Run WQNet= 0
Run RASMapper=-1
UNET Theta= 0
UNET Theta Warmup= 0
UNET ZTol= 0
UNET ZSATol= 0
UNET MxIter= 0
UNET Max Iter WO Improvement= 0
UNET MaxInSteps= 0
UNET DtIC= 0
UNET DtMin= 0
UNET MaxCRTS= 0
UNET WFStab= 0
UNET SFStab= 0
UNET WFX= 1
UNET SFX= 1
UNET Gravity=32.174
UNET 1D Methodology=Finite Difference
UNET DSS MLevel= 1
UNET Pardiso=0
UNET DZMax Abort= 0
UNET Use Existing IB Tables= 0
UNET Froude Reduction=False
UNET Froude Limit= 0
UNET Froude Power= 0
UNET D1 Cores= 0
UNET WindReference=Eulerian
UNET WindDragFormulation=Hsu (1988)
UNET D2 Coriolis=0
UNET D2 Cores= 0
UNET D2 Theta= 1
UNET D2 Theta Warmup= 1
UNET D2 Z Tol= 0.01
UNET D2 Volume Tol= 0.01
UNET D2 Max Iterations= 20
UNET D2 Equation= 0
UNET D2 RampUpFraction=0.1
UNET D2 TimeSlices= 1
UNET D2 Turbulence Formulation=Non-Conservative (original)
UNET D2 Eddy Viscosity=0.3
UNET D2 Transverse Eddy Viscosity=0.1
UNET D2 Smagorinsky Mixing=0
UNET D2 BCVolumeCheck=0
UNET D2 Cores=0
UNET D2 SolverType=PARDISO (Direct)
UNET D2 Minimum Iterations= 2147483647
UNET D2 Maximum Iterations= 2147483647
UNET D2 Restart Number= 10
UNET D2 Relaxation Coeff=1.3
UNET D2 SOR Precondition Iterations= 10
UNET D2 ILUT Maximum Fill= 8
UNET D2 ILUT Tolerance=1E-08
UNET D1D2 MaxIter= 0
UNET D1D2 ZTol=0.01
UNET D1D2 QTol=0.1
UNET D1D2 MinQTol=1
Write IC File= 0
Write IC File at Fixed DateTime=0
Write IC File at Sim End=0
Echo Input=False
Echo Parameters=False
Echo Output=False
Write Detailed= 0
HDF Write Warmup=0
HDF Write Time Slices=0
HDF Flush=0
HDF Compression= 1
HDF Chunk Size= 1
HDF Spatial Parts= 1
HDF Use Max Rows=0
HDF Fixed Rows= 1
Calibration Method= 0
Calibration Iterations= 20
Calibration Max Change=0.05
Calibration Tolerance=0.2
Calibration Maximum=1.5
Calibration Minimum=0.5
Calibration Optimization Method= 1
WQ AD Non Conservative
WQ ULTIMATE=-1
WQ Max Comp Step=1HOUR
WQ Output Interval=15MIN
WQ Output Selected Increments= 0
WQ Output face flow=0
WQ Output face velocity=0
WQ Output face area=0
WQ Output face dispersion=0
WQ Output cell volume=0
WQ Output cell surface area=0
WQ Output cell continuity=0
WQ Output cumulative cell continuity=0
WQ Output face conc=0
WQ Output face dconc_dx=0
WQ Output face courant=0
WQ Output face peclet=0
WQ Output face adv mass=0
WQ Output face disp mass=0
WQ Output cell mass=0
WQ Output cell source sink temp=0
WQ Output nsm pathways=0
WQ Output nsm derived pathways=0
WQ Create Restart=0
WQ Fixed Restart=0
WQ System Summary=0
WQ Write To DSS=0
Sorting and Armoring Iterations= 10
XS Update Threshold= 0.02
Bed Roughness Predictor= 0
Hydraulics Update Threshold= 0.02
Energy Slope Method= 1
Volume Change Method= 1
Sediment Retention Method= 0
Sediment TS Multiplier= 1
Warm Up Method= 0
XS Weighting Method= 0
Number of US Weighted Cross Sections= 1
Number of DS Weighted Cross Sections= 1
Upstream XS Weight=0
Main XS Weight=1
Downstream XS Weight=0
Number of DS XS's Weighted with US Boundary= 1
Upstream Boundary Weight= 1
Weight of XSs Associated with US Boundary= 0
Number of US XS's Weighted with DS Boundary= 1
Downstream Boundary Weight= 0.5
Weight of XSs Associated with DS Boundary= 0.5
Percentile Method= 0
Sediment Output Level= 3
Mass or Volume Output= 0
Output Increment Type= 1
Profile and TS Output Increment= 1
Transport Output Increment 1
XS Output Flag= 0
XS Output Increment= 10
Read HDF5 Sediment Hotstart= 0
Sediment Hotstart Type= 0
Write Gradation File= 0
Read Gradation Hotstart= 0
Write HDF5 File= 1
Write Binary Output= 1
Write DSS Sediment File= 0
DSS Sediment Output Type= 1
SV Curve= 0
Specific Gage Flag= 0
Subcell Erosion Methods= 0
Subcell Deposition Methods= 0
Advection Scheme= 1
Matrix Solver= 0
Implicit Weighting Factor= 1
Maximum Outer Loop Convergence Iterations= 5
Convergence Maximum Absolute= 0.001
Convergence RMSE= 0.0001
Grain Fractions Max Abs Error= 0.001
Max Subgrid Regions= 1
Max Subgrid Length Scale= 3.402823E+38
Initial Layer Thickness= 3.402823E+38
Min Layer Thickness= 3.402823E+38
Max Layer Thickness= 3.402823E+38
Number of Layers= 5

--- BRNGRN.f01 (steady flow) ---

Flow Title=Flow
Program Version=6.10
Number of Profiles= 6
Profile Names=01pct,10pct,04pct,02pct,0_2pct,01plus
River Rch & RM=BRNGRN,Main            ,5701
     597     316     420     505     833     882
Boundary for River Rch & Prof#=BRNGRN,Main            , 1
Up Type= 0
Dn Type= 3
Dn Slope=0.02323
Boundary for River Rch & Prof#=BRNGRN,Main            , 2
Up Type= 0
Dn Type= 3
Dn Slope=0.02323
Boundary for River Rch & Prof#=BRNGRN,Main            , 3
Up Type= 0
Dn Type= 3
Dn Slope=0.02323
Boundary for River Rch & Prof#=BRNGRN,Main            , 4
Up Type= 0
Dn Type= 3
Dn Slope=0.02323
Boundary for River Rch & Prof#=BRNGRN,Main            , 5
Up Type= 0
Dn Type= 3
Dn Slope=0.02323
Boundary for River Rch & Prof#=BRNGRN,Main            , 6
Up Type= 0
Dn Type= 3
Dn Slope=0.02323
DSS Import GetInterval= 0
DSS Import GetPeak= 0
DSS Import FillOption= 0

--- BRNGRN.g01 (geometry) ---

Geom Title=Geometry
Program Version=6.10

River Reach=BRNGRN          ,Main
Reach XY= 30
2352848.32800613595103.4519151452352758.20909189595156.865850315
2352626.79662505595103.5224530552352647.16436647595205.362144396
2352542.29121664595163.3264673052352463.85272522595267.766219065
2352362.87983005595131.2576338052351917.89384338595256.410926804
2351814.11331699595208.5292281622351672.16598839595320.170969889
2351439.67892055595249.308578804 2351356.5344018595321.733630806
2351247.07431889595220.9529924842351267.93287297595112.338052228
2351063.88505273595187.2749102262350991.83499996595164.893065229
2350947.34854038595234.6376763882350794.47187763595102.127114639
2350547.83818455595079.5786033122350344.82776381594895.049772888
2350322.91999923594803.4279088972350094.00608698594666.493143395
2349956.51292364594628.6700563132349787.73865488594669.169319138
2349701.80838056594562.3883647322349366.26049522594547.483210817
2349238.31291647594650.6089888072349076.68725547594700.493403479
2348964.09332055 594827.019397142348567.85395555594815.692976221

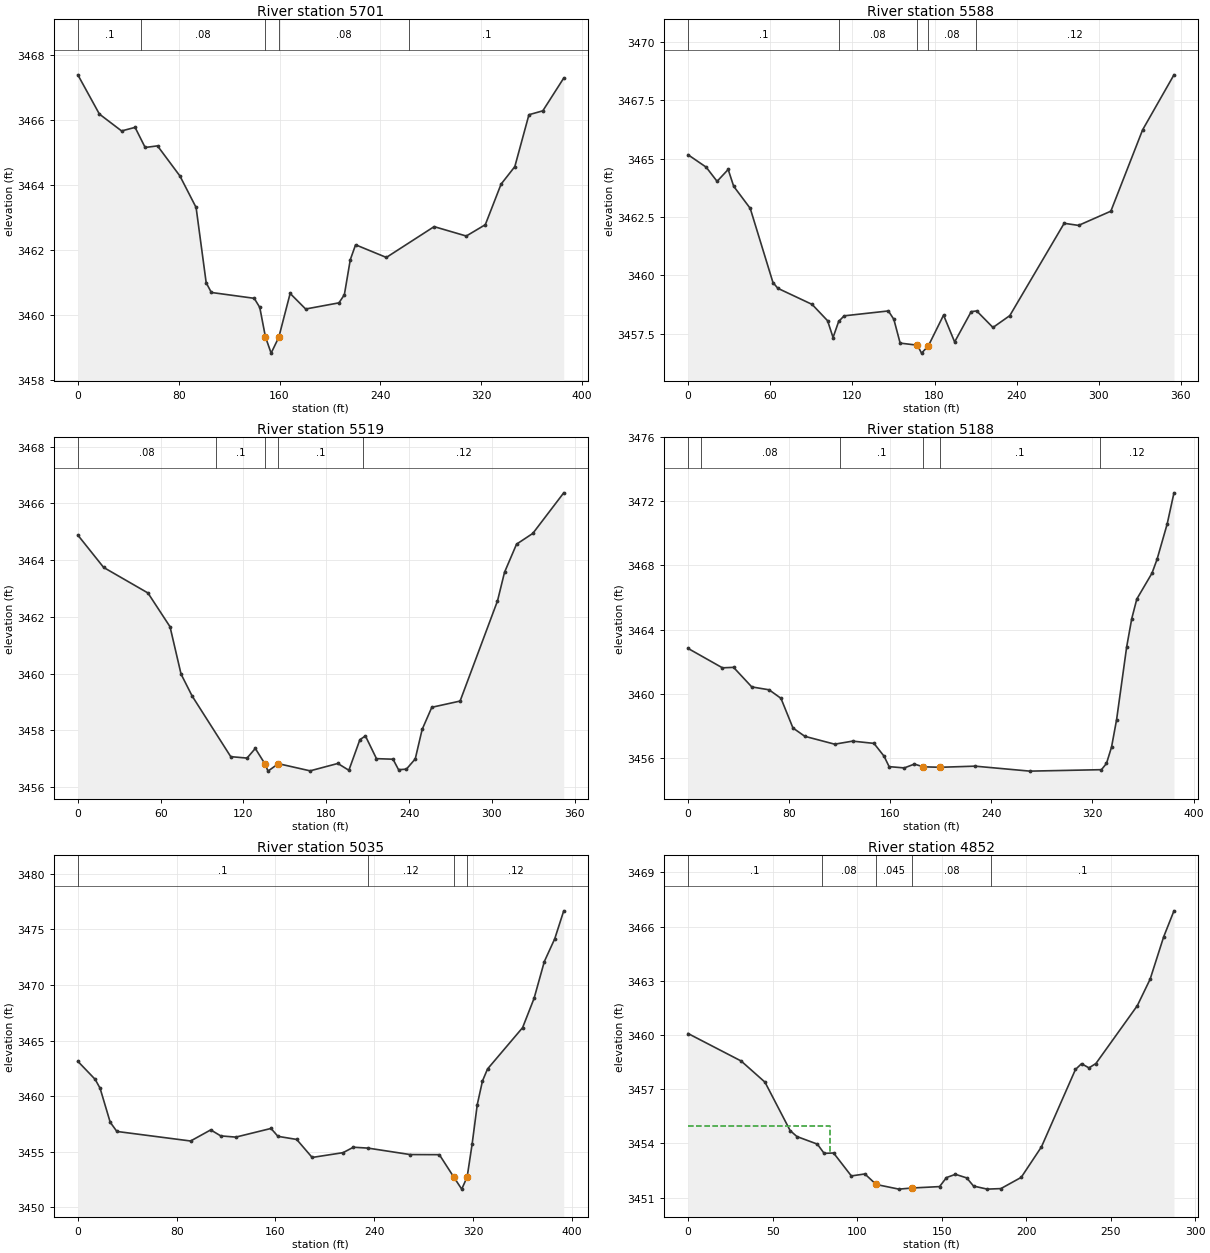
Type RM Length L Ch R = 1 ,5701    ,113.2,113.2,113.2
XS GIS Cut Line= 4
2352842.18552533594952.2195276812352826.10830712595073.498512716
2352870.86424067595163.2156572892352983.02136546595281.182614443
#Sta/Elev= 30
       0  3467.4    17.1 3466.19    34.7 3465.67    45.4 3465.78    53.4 3465.16
    63.2 3465.21      81 3464.28    93.8 3463.31   101.8 3460.99   105.9 3460.69
   139.9 3460.51   144.3 3460.23   148.8 3459.32   153.3 3458.82   159.4 3459.31
   168.4 3460.66   180.7 3460.18   207.1 3460.37   211.4 3460.62   216.1  3461.7
   220.3 3462.16   244.7 3461.77   282.6 3462.72   308.1 3462.43   323.2 3462.78
   335.7 3464.03   346.6 3464.57   357.8 3466.17   368.8 3466.29   385.4  3467.3
#Mann= 5 ,-1,0
       0      .1       0      50     .08       0   148.8    .045       0
   159.4     .08       0   262.6      .1       0
Bank Sta=148.8,159.4
XS Rating Curve= 0 ,0
Exp/Cntr=0.3,0.1

Type RM Length L Ch R = 1 ,5588    ,64.4,69.2,75.7
XS GIS Cut Line= 3
2352723.74094989594988.1373316662352757.11298047595246.012113456
 2352802.6202949595329.273644308
#Sta/Elev= 30
       0 3465.17    13.2 3464.64    21.2 3464.03    29.3 3464.54    33.3 3463.82
    45.4 3462.87      62 3459.69    65.6 3459.44    90.6 3458.75   101.9 3458.05
   105.9 3457.33     110 3458.02     114 3458.26   146.3 3458.47   150.3 3458.11
   154.9 3457.09   167.5    3457   170.5 3456.66   175.4 3456.96   186.6 3458.29
   194.7 3457.14   206.8 3458.44   210.8 3458.47   222.7 3457.76     235 3458.27
   274.7 3462.23   285.2 3462.14   308.8 3462.75     332 3466.24   354.9  3468.6
#Mann= 5 ,-1,0
       0      .1       0     110     .08       0   167.5    .045       0
   175.4     .08       0     210     .12       0
Bank Sta=167.5,175.4
XS Rating Curve= 0 ,0
Exp/Cntr(USF)=0,0
Exp/Cntr=0.3,0.1

Type RM Length L Ch R = 1 ,5519    ,324.7,330.3,318.1
XS GIS Cut Line= 5
2352703.95970942594994.4658346472352698.45910853595109.827261374
2352677.93163082595145.550666493 2352684.6383686595265.563404101
2352647.31101912595330.862185276
#Sta/Elev= 30
       0 3464.88    18.7 3463.74    50.8 3462.84    66.8 3461.65    74.8 3459.98
    82.8 3459.21   110.8 3457.07   122.6 3457.02   128.6 3457.36  135.65 3456.81
   137.8 3456.56   145.33456.823   168.3 3456.57   188.4 3456.83   196.4 3456.59
   204.4 3457.67   208.4  3457.8   216.4    3457   228.4 3456.98   232.4 3456.61
   238.1 3456.63   244.5 3456.99   249.5 3458.03   256.5 3458.81     277 3459.03
   304.1 3462.56   309.2 3463.57   317.9 3464.56   329.7 3464.94   352.1 3466.37
#Mann= 5 ,-1,0
       0     .08       0     100      .1       0  135.65    .045       0
   145.3      .1       0  206.69     .12       0
Bank Sta=135.65,145.3
XS Rating Curve= 0 ,0
Exp/Cntr(USF)=0,0
Exp/Cntr=0.3,0.1

Type RM Length L Ch R = 1 ,5188    ,149.1,152.9,153.1
XS GIS Cut Line= 3
2352623.28776691594990.8340614112352551.15024626595106.119257975
 2352544.4084219 595354.55548566
#Sta/Elev= 30
       0 3462.83    27.2 3461.62      36 3461.65    50.4 3460.43    64.1 3460.25
    73.5 3459.72      83 3457.87    92.4 3457.35     116 3456.86   130.2 3457.05
   147.1 3456.91   155.1 3456.11   159.1 3455.46   171.1 3455.38   179.1 3455.62
     1863455.449   199.6 3455.42   227.1 3455.49   270.4 3455.18   327.1 3455.27
   331.1 3455.66   335.1 3456.68   339.1 3458.39   347.1 3462.94   351.1 3464.69
   355.1 3465.91   367.1 3467.52   371.1 3468.38   379.1 3470.58   384.5 3472.53
#Mann= 6 ,-1,0
       0      .1       0      10     .08       0     120      .1       0
     186    .045       0   199.6      .1       0  325.99     .12       0
Bank Sta=186,199.6
XS Rating Curve= 0 ,0
Exp/Cntr(USF)=0,0
Exp/Cntr=0.3,0.1

Type RM Length L Ch R = 1 ,5035    ,183.9,183.7,168.7
XS GIS Cut Line= 4
2352472.98159641594963.4502329842352501.73005594595117.248676463
2352482.48427144595183.0309618422352433.60652021595344.195438869
#Sta/Elev= 30
       0 3463.13      14 3461.51      18 3460.71    26.2 3457.65    31.6 3456.82
    91.3 3455.96   107.6 3456.96   115.7 3456.42   127.9 3456.31   156.4 3457.09
     162 3456.38   177.2  3456.1   189.7 3454.48   214.7 3454.91   223.1  3455.4
     235 3455.32     269 3454.74   292.7 3454.73   304.53452.695   310.8 3451.63
   315.2 3452.72   319.2 3455.66   323.4 3459.24   327.6 3461.36   331.7 3462.44
   360.1 3466.16   369.4  3468.8   377.7 3472.11   386.1 3474.15   393.4 3476.67
#Mann= 4 ,-1,0
       0      .1       0     235     .12       0   304.5    .045       0
   315.2     .12       0
Bank Sta=304.5,315.2
XS Rating Curve= 0 ,0
Exp/Cntr(USF)=0,0
Exp/Cntr=0.3,0.1

Type RM Length L Ch R = 1 ,4852    ,152.1,151.4,145.6
XS GIS Cut Line= 3
2352406.18113758595023.3958201712352372.33187048595071.922156153
2352350.47083555595299.253560503
#Sta/Elev= 30
       0 3460.08    31.4 3458.56    45.5 3457.39    60.4 3454.71    64.4 3454.38
    76.5 3453.96    80.5 3453.45    86.1 3453.47    96.6  3452.2   104.6 3452.31
   111.33451.728   124.7 3451.47   132.73451.533   148.8 3451.61   152.9 3452.11
   158.2 3452.29   164.9 3452.09   168.9 3451.64     177 3451.47   185.1  3451.5
   197.1 3452.12   209.1 3453.81   229.2 3458.09   232.8 3458.41   237.2 3458.18
   241.3 3458.42   265.8 3461.62   273.4 3463.09   281.4 3465.43   287.5 3466.87
#Mann= 5 ,-1,0
       0      .1       0   79.17     .08       0   111.3    .045       0
   132.7     .08       0  179.17      .1       0
#XS Ineff= 2 , 0
           84.17 3454.97
Permanent Ineff=
       F       F
Bank Sta=111.3,132.7
XS Rating Curve= 0 ,0
Exp/Cntr(USF)=0,0
Exp/Cntr=0.3,0.1

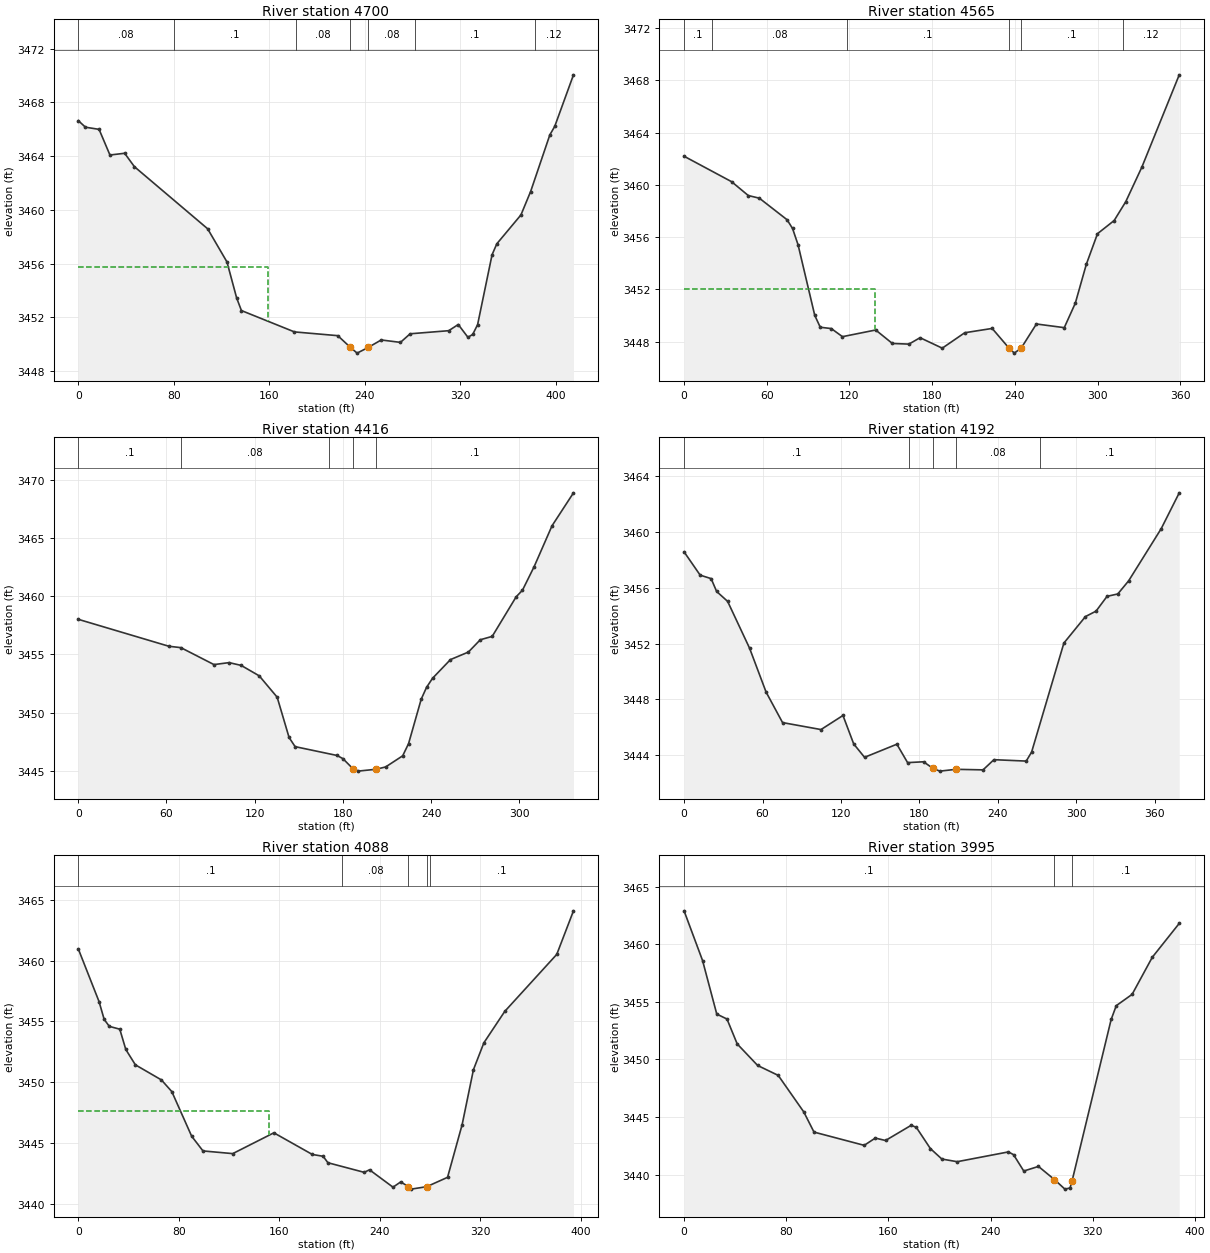
Type RM Length L Ch R = 1 ,4700    ,137.4,135,135.7
XS GIS Cut Line= 3
2352196.40998571594915.3041803312352218.50038078595015.187993279
2352260.40608041595324.747084401
#Sta/Elev= 30
       0 3466.65       6 3466.16    17.4    3466    26.5 3464.09    38.8 3464.22
      47 3463.22   108.3  3458.6   124.5 3456.13   132.6 3453.45   136.6 3452.51
     181 3450.92   217.3 3450.64   227.73449.784   233.5 3449.34   242.7 3449.76
   253.7 3450.32   269.8 3450.14   277.9 3450.78   310.2 3451.01   318.2 3451.47
   326.3 3450.52   330.3 3450.73   334.4 3451.46   346.5 3456.66   350.5 3457.48
   370.7 3459.63   378.8 3461.37   394.9 3465.59     399 3466.22   414.7 3470.06
#Mann= 7 ,-1,0
       0     .08       0      80      .1       0   182.3     .08       0
   227.7    .045       0   242.7     .08       0   282.3      .1       0
   382.3     .12       0
#XS Ineff= 2 , 0
          158.64 3455.76
Permanent Ineff=
       F       F
Bank Sta=227.7,242.7
XS Rating Curve= 0 ,0
Exp/Cntr(USF)=0,0
Exp/Cntr=0.3,0.1

Type RM Length L Ch R = 1 ,4565    ,148.3,149.4,145.5
XS GIS Cut Line= 3
2352106.13491241594978.6889767972352109.25987114595036.916994086
2352140.60018273595336.154634807
#Sta/Elev= 30
       0 3462.19    34.5 3460.24    46.6 3459.18    54.6 3458.98    74.7 3457.33
    78.7 3456.66    82.7 3455.41    94.8 3450.01    98.8  3449.1   106.8    3449
   114.9 3448.38     139 3448.89   151.1 3447.86   163.1 3447.81   171.2  3448.3
   187.3  3447.5   203.6 3448.68   223.5 3449.01   235.5 3447.53   239.6 3447.12
   244.63447.514   255.6 3449.35   275.8 3449.07   283.8 3450.94   291.8 3453.92
   299.9 3456.26     312 3457.27   320.4 3458.71   332.1 3461.36   359.2 3468.42
#Mann= 6 ,-1,0
       0      .1       0      20     .08       0  118.31      .1       0
   235.5    .045       0   244.6      .1       0  318.31     .12       0
#XS Ineff= 2 , 0
          138.37    3452
Permanent Ineff=
       F       F
Bank Sta=235.5,244.6
XS Rating Curve= 0 ,0
Exp/Cntr(USF)=0,0
Exp/Cntr=0.3,0.1

Type RM Length L Ch R = 1 ,4416    ,221,223.6,215.1
XS GIS Cut Line= 3
2352006.88401974595033.1715361082351979.83348989595150.529219421
2352018.12039367595363.604162173
#Sta/Elev= 30
       0 3458.03    61.6 3455.71    69.8 3455.59    92.3 3454.13   102.6  3454.3
   110.8 3454.06   123.1 3453.16   135.3 3451.32   143.4 3447.85   147.5 3447.06
     176  3446.3     180 3446.03  187.14 3445.12   190.2 3444.95   202.6 3445.11
   209.1 3445.31   220.7 3446.27   224.7 3447.32   233.3 3451.15   236.9 3452.16
     241 3452.95   253.2 3454.56   265.4 3455.21   273.5 3456.27   281.6 3456.56
   297.9 3459.97   302.2 3460.54   310.1 3462.56   322.3 3466.09   336.9 3468.93
#Mann= 5 ,-1,0
       0      .1       0      70     .08       0  170.43      .1       0
  187.14    .045       0   202.6      .1       0
Bank Sta=187.14,202.6
XS Rating Curve= 0 ,0
Exp/Cntr(USF)=0,0
Exp/Cntr=0.3,0.1

Type RM Length L Ch R = 1 ,4192    ,95.6,104.2,92.9
XS GIS Cut Line= 3
2351818.77879684 595029.426078132351781.74037905595145.951437447
2351843.33235469 595394.81631199
#Sta/Elev= 30
       0 3458.58    12.3 3456.91    20.7 3456.66    24.9 3455.74    33.3 3455.03
    50.1 3451.67    62.7 3448.53    75.3 3446.34   104.7 3445.84   121.5 3446.85
   129.7 3444.81     138 3443.85   162.7 3444.79   170.9 3443.47   183.1 3443.53
  190.39 3443.05   195.6 3442.86     208 3442.99   228.6 3442.95   236.9 3443.68
   261.6 3443.58   265.7 3444.22   290.4 3452.04   306.9 3453.94     315 3454.33
   323.4 3455.39   331.6 3455.56   339.9  3456.5   364.8 3460.24   378.6 3462.81
#Mann= 5 ,-1,0
       0      .1       0  172.27     .08       0  190.39    .045       0
     208     .08       0  272.27      .1       0
Bank Sta=190.39,208
XS Rating Curve= 0 ,0
Exp/Cntr(USF)=0,0
Exp/Cntr=0.3,0.1

Type RM Length L Ch R = 1 ,4088    ,91.1,93.2,95.1
XS GIS Cut Line= 2
2351669.79280171595025.2644581542351770.92016712595406.052685924
#Sta/Elev= 30
       0 3460.96    16.5 3456.63    20.6 3455.16    24.7 3454.59      33 3454.36
    37.8 3452.69    45.4 3451.43    66.1 3450.19    74.4 3449.23    90.2 3445.56
    99.2 3444.35   122.9 3444.13   155.6 3445.84   186.2 3444.06   194.8 3443.91
   198.6 3443.38   227.5 3442.59   231.7  3442.8   250.4 3441.37   256.5  3441.8
   262.7 3441.42   264.8 3441.21   277.2 3441.41   293.8 3442.18   305.4 3446.51
   314.4 3451.03   322.7 3453.24   339.3 3455.82   380.7 3460.51     394 3464.09
#Mann= 5 ,-1,0
       0      .1       0     210     .08       0   262.7    .045       0
   277.2     .08       0     280      .1       0
#XS Ineff= 2 , 0
           151.5 3447.62
Permanent Ineff=
       F       F
Bank Sta=262.7,277.2
XS Rating Curve= 0 ,0
Exp/Cntr(USF)=0,0
Exp/Cntr=0.3,0.1

Type RM Length L Ch R = 1 ,3995    ,324.1,327.6,325.8
XS GIS Cut Line= 3
2351638.58065189595023.5998101642351649.81702583595273.297008701
2351664.38269574  595410.2143059
#Sta/Elev= 30
       0 3462.89    14.5 3458.57    25.6 3453.93    33.6  3453.5    41.6 3451.34
    57.6 3449.47    73.7 3448.61    93.7 3445.44   101.7 3443.69     141 3442.54
   149.7 3443.17   157.7 3442.96   177.8 3444.28   181.8  3444.1   192.8 3442.26
   201.8 3441.35   213.8 3441.12   253.9 3441.97   257.9 3441.73   265.9 3440.31
   277.4 3440.71   289.93439.571   298.1 3438.74   302.1 3438.84   303.63439.402
   334.3 3453.46   338.3 3454.66   350.7 3455.64   366.5 3458.86   387.6  3461.8
#Mann= 3 ,-1,0
       0      .1       0   289.9    .045       0   303.6      .1       0
Bank Sta=289.9,303.6
XS Rating Curve= 0 ,0
Exp/Cntr(USF)=0,0
Exp/Cntr=0.3,0.1

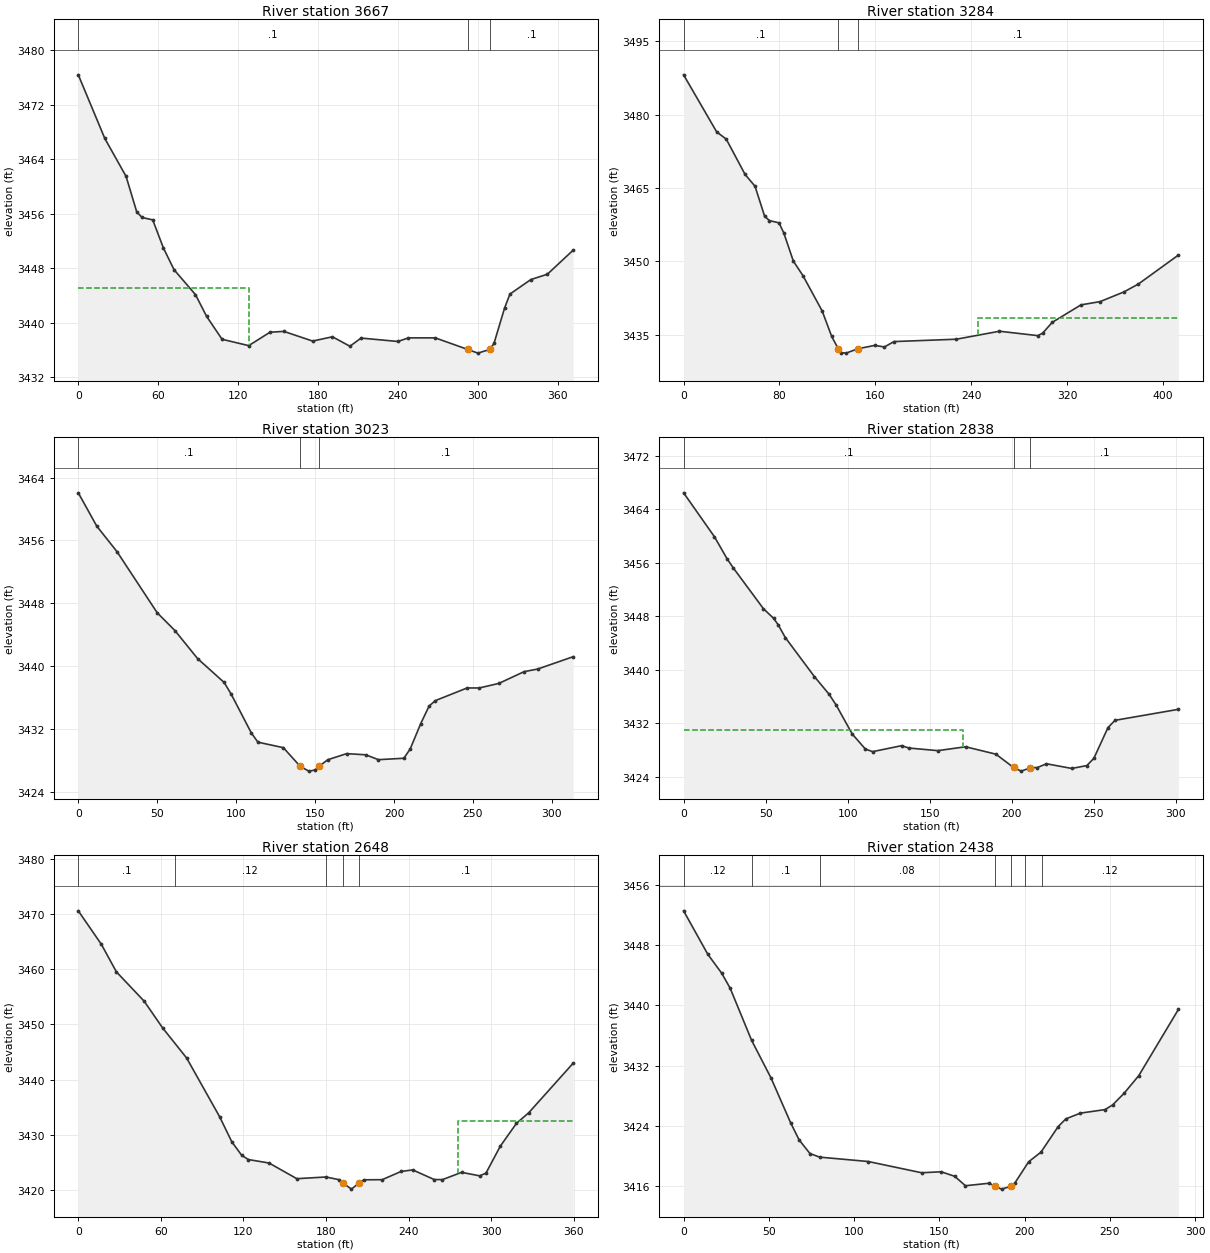
Type RM Length L Ch R = 1 ,3667    ,369,383.2,367.7
XS GIS Cut Line= 3
 2351391.9820109595013.2798528412351382.73486877595278.804933845
2351390.00048044595384.486558126
#Sta/Elev= 30
       0 3476.41    19.9 3467.08    35.9  3461.5    43.9 3456.29    47.9 3455.47
    55.9 3455.12    63.9 3451.01    71.9 3447.81      88 3444.15    96.4 3440.95
     108 3437.59     128 3436.66     144 3438.63   154.4 3438.75     176 3437.33
   190.9 3437.96     204 3436.57   212.4 3437.77     240 3437.27     248  3437.8
   268.1  3437.8   292.5  3436.1   300.1 3435.56   309.13436.104   312.2 3436.98
   320.2  3442.2   324.2 3444.23   339.9 3446.36   352.3 3447.14   371.6 3450.66
#Mann= 3 ,-1,0
       0      .1       0   292.5    .045       0   309.1      .1       0
#XS Ineff= 2 , 0
          128.24 3445.12
Permanent Ineff=
       F       F
Bank Sta=292.5,309.1
XS Rating Curve= 0 ,0
Exp/Cntr(USF)=0,0
Exp/Cntr=0.3,0.1

Type RM Length L Ch R = 1 ,3284    ,260.4,261.5,257.7
XS GIS Cut Line= 2
 2351223.5519222594977.6123046472351230.81753387595390.431149491
#Sta/Elev= 30
       0  3488.1    27.6 3476.45    35.6 3474.97    51.3 3467.77    59.6 3465.35
    67.6 3459.25    71.6 3458.34    79.6 3457.88    83.6 3455.83    91.6 3450.06
    99.6  3447.1   115.6 3439.91   123.6 3434.68   129.2 3432.12   131.6 3431.38
   135.6 3431.28   145.5 3432.18   159.6 3432.86   167.6 3432.54   175.6 3433.64
   227.6 3434.12   263.6 3435.75   295.6 3434.85   299.6 3435.35   307.6 3437.56
   331.6 3441.13   347.6  3441.8   367.6 3443.79   379.6  3445.4   412.9  3451.3
#Mann= 3 ,-1,0
       0      .1       0   129.2    .045       0   145.5      .1       0
#XS Ineff= 1 ,-1
  245.92412.8828 3438.52
Permanent Ineff=
       F
Bank Sta=129.2,145.5
XS Rating Curve= 0 ,0
Exp/Cntr(USF)=0,0
Exp/Cntr=0.3,0.1

Type RM Length L Ch R = 1 ,3023    ,178.6,185,189
XS GIS Cut Line= 3
2351031.61050122595022.1947097922350992.77412838595128.658808782
 2351009.5310546595327.979380073
#Sta/Elev= 30
       0 3462.07    11.7 3457.83    24.5 3454.58      50 3446.78    61.2 3444.52
    75.6 3440.94    92.4  3437.9    96.8 3436.43   109.6 3431.47   113.8 3430.29
   129.9 3429.59  140.55 3427.21     146  3426.6     150 3426.74   152.63427.218
     158 3428.05     170 3428.83   182.1 3428.68   190.1 3428.06   206.2 3428.24
   210.2 3429.41   216.9 3432.65   222.2 3434.89   226.2 3435.59   246.3  3437.2
     254  3437.2   266.4 3437.78   282.4 3439.28     291 3439.61   313.4 3441.18
#Mann= 3 ,-1,0
       0      .1       0  140.55    .045       0   152.6      .1       0
Bank Sta=140.55,152.6
XS Rating Curve= 0 ,0
Exp/Cntr(USF)=0,0
Exp/Cntr=0.3,0.1

Type RM Length L Ch R = 1 ,2838    ,188.4,189.8,188.9
XS GIS Cut Line= 3
2350977.16607064595001.1550245072350903.39604655595156.326536406
 2350855.7600544595277.054581943
#Sta/Elev= 30
       0 3466.45    18.8 3459.89    26.6 3456.56    30.3 3455.23    48.7 3449.13
    54.8 3447.72    57.6 3446.76      62 3444.83    79.7 3439.01    88.6 3436.39
      93 3434.75   102.8 3430.42   110.8 3428.18   115.2 3427.79   132.9 3428.68
   137.3 3428.33     155 3427.94   171.9 3428.52   190.4 3427.41   201.13425.427
   205.8 3424.88   211.4 3425.37   215.7 3425.42   221.2 3425.98   236.6 3425.28
   245.8 3425.71   250.1  3426.8   258.7 3431.39     263 3432.47   301.6 3434.11
#Mann= 3 ,-1,0
       0      .1       0   201.1    .045       0   211.4      .1       0
#XS Ineff= 2 , 0
          170.17 3430.99
Permanent Ineff=
       F       F
Bank Sta=201.1,211.4
XS Rating Curve= 0 ,0
Exp/Cntr(USF)=0,0
Exp/Cntr=0.3,0.1

Type RM Length L Ch R = 1 ,2648    ,207.3,210.3,210.8
XS GIS Cut Line= 2
2350829.88787176594937.9816955422350674.66798609595262.292180052
#Sta/Elev= 30
       0 3470.59    16.8 3464.51    27.7 3459.53    47.9 3454.21    61.2  3449.4
    78.7 3443.93   102.7 3433.28   111.6 3428.71   118.8 3426.27   123.6 3425.52
   138.6 3424.89   158.8 3422.05     180 3422.36   189.3 3421.88   192.6 3421.22
   198.5 3420.16   203.83421.236   207.5 3421.85   220.8 3421.87   234.6 3423.37
     243 3423.64   258.6  3421.9   264.6 3421.88   278.5  3423.2   291.6 3422.57
   296.2 3423.05   306.6 3427.93   318.4 3432.09   327.3    3434   359.5 3442.96
#Mann= 5 ,-1,0
       0      .1       0      70     .12       0     180      .1       0
   192.6    .045       0   203.8      .1       0
#XS Ineff= 2 , 0
                          275.75         3432.59
Permanent Ineff=
       F       F
Bank Sta=192.6,203.8
XS Rating Curve= 0 ,0
Exp/Cntr(USF)=0,0
Exp/Cntr=0.3,0.1

Type RM Length L Ch R = 1 ,2438    ,156.8,157.5,156.5
XS GIS Cut Line= 3
2350662.50406883 594931.575153092350527.19834822595106.018726304
 2350502.3433106595170.870685734
#Sta/Elev= 30
       0 3452.53    14.2 3446.77    22.3 3444.28    27.3 3442.28    39.9 3435.36
    51.3 3430.37    62.8 3424.43    67.8 3422.16    74.1 3420.37    79.8 3419.89
   108.3 3419.31   139.6 3417.82   151.1 3417.95     159 3417.35   165.3  3416.1
   179.2 3416.43   182.4 3416.07   186.5 3415.65     1923416.027   194.4  3416.5
   202.4 3419.28   209.6 3420.55   219.7 3423.94   224.2 3424.96   232.7 3425.72
   247.2 3426.19   251.6  3426.8   258.4 3428.36     267  3430.7   290.2 3439.46
#Mann= 7 ,-1,0
       0     .12       0      40      .1       0      80     .08       0
   182.4    .045       0     192     .08       0     200      .1       0
     210     .12       0
Bank Sta=182.4,192
XS Rating Curve= 0 ,0
Exp/Cntr(USF)=0,0
Exp/Cntr=0.3,0.1

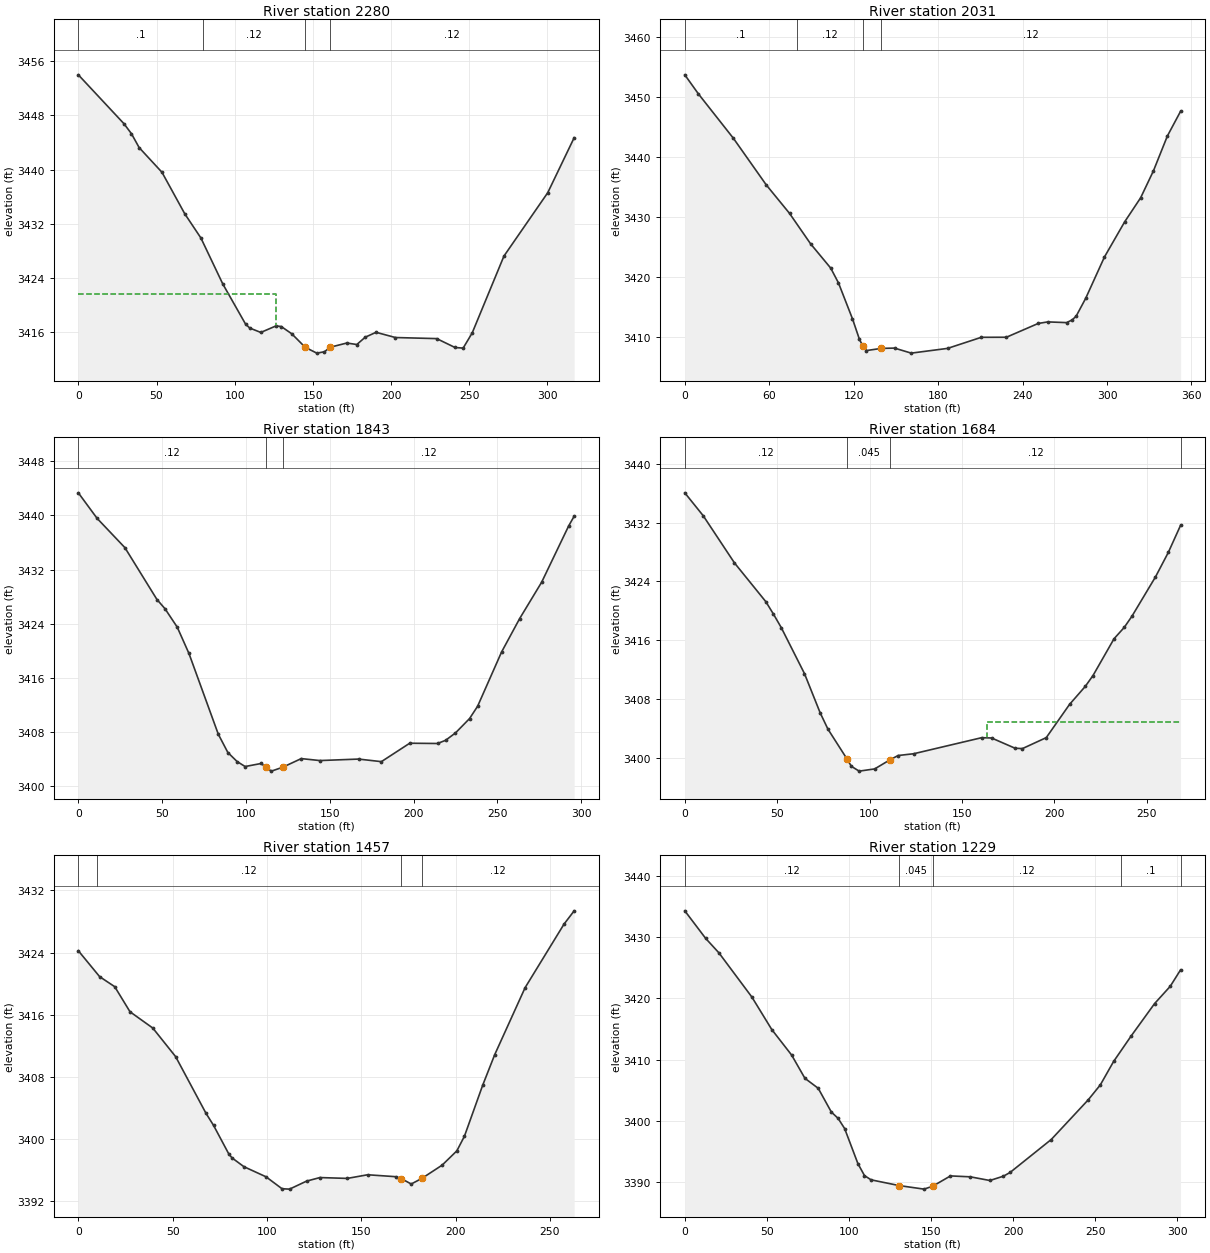
Type RM Length L Ch R = 1 ,2280    ,248.8,248.8,248.4
XS GIS Cut Line= 3
2350544.78532219594833.2077065492350469.76441606594941.661842577
2350350.70949982595083.549208509
#Sta/Elev= 30
       0 3453.98    29.2 3446.77      34 3445.29    38.9 3443.25    53.5 3439.61
    68.1 3433.48    78.4 3429.92    92.4 3423.14     107 3417.21   109.7 3416.64
   116.7    3416   126.4 3416.96   129.8 3416.87   136.5  3415.8   145.13413.809
   152.5 3412.95   157.4 3413.15   161.1 3413.82   171.7 3414.44   178.1 3414.22
   183.5  3415.3   190.4 3416.02   202.8 3415.25   229.2 3415.09   240.9 3413.78
   246.1 3413.69   251.9 3415.93   272.2 3427.26   300.2  3436.6   317.1 3444.71
#Mann= 4 ,-1,0
       0      .1       0      80     .12       0   145.1    .045       0
   161.1     .12       0
#XS Ineff= 2 , 0
          126.59 3421.62
Permanent Ineff=
       F       F
Bank Sta=145.1,161.1
XS Rating Curve= 0 ,0
Exp/Cntr(USF)=0,0
Exp/Cntr=0.3,0.1

Type RM Length L Ch R = 1 ,2031    ,188.9,188.6,187.6
XS GIS Cut Line= 2
2350385.40465607594681.3648273112350176.08677892594964.683974156
#Sta/Elev= 30
       0 3453.76     9.7 3450.57    34.6 3443.15    57.9 3435.39    74.4 3430.65
    89.4 3425.56   103.7 3421.51   109.2 3419.04   119.1 3413.08   124.1 3409.62
   126.6 3408.47   129.1 3407.76   139.6 3408.12     149 3408.17   160.9 3407.33
   186.7 3408.12   210.7 3409.97   228.5 3409.98   251.1 3412.28   257.9 3412.54
   271.3 3412.42   275.3 3412.88   278.1 3413.51   284.8 3416.45   298.2 3423.38
   312.5 3429.22   323.9 3433.25     333 3437.75   342.9 3443.56   352.3 3447.69
#Mann= 4 ,-1,0
       0      .1       0      80     .12       0   126.6    .045       0
   139.6     .12       0
Bank Sta=126.6,139.6
XS Rating Curve= 0 ,0
Exp/Cntr(USF)=0,0
Exp/Cntr=0.3,0.1

Type RM Length L Ch R = 1 ,1843    ,161.9,158.7,155.5
XS GIS Cut Line= 2
2350208.50638279594605.9540096192350046.40836345 594853.32968261
#Sta/Elev= 30
       0 3443.34    11.2 3439.57    27.8 3435.24    46.9 3427.59    51.7 3426.23
      59 3423.51      66 3419.62    83.5  3407.7    89.2    3405    94.7 3403.67
    99.5 3402.93   109.1 3403.38  111.87 3402.81   115.2 3402.25  121.99 3402.83
     133  3404.1   144.1 3403.81   167.2 3404.03   180.8 3403.65   197.7 3406.37
   214.3 3406.33   219.1  3406.8     225 3407.89   233.4 3410.01   238.2 3411.83
   252.5 3419.84   263.3 3424.78   276.4 3430.14   292.5 3438.44   295.8 3439.89
#Mann= 3 ,-1,0
       0     .12       0  111.87    .045       0  121.99     .12       0
Bank Sta=111.87,121.99
XS Rating Curve= 0 ,0
Exp/Cntr(USF)=0,0
Exp/Cntr=0.3,0.1

Type RM Length L Ch R = 1 ,1684    ,231.6,227.1,219.5
XS GIS Cut Line= 2
2350034.31698268594543.7248622632349948.69529635594798.143587382
#Sta/Elev= 30
       0 3436.04      10 3432.92    26.9 3426.52    43.9 3421.25      48 3419.57
    52.2 3417.75    64.8 3411.49    73.3 3406.16    77.5 3403.95    87.73399.947
    90.2  3398.9    94.4 3398.25   102.8 3398.55   111.3 3399.82   115.5 3400.37
   123.9 3400.61   160.7 3402.79   166.1 3402.75   178.8 3401.36   182.8 3401.31
   195.7  3402.8   208.3 3407.31   216.8 3409.75     221 3411.23   232.4 3416.23
   237.9 3417.76   242.1 3419.29   254.8 3424.61   261.8 3427.96   268.4 3431.62
#Mann= 4 ,-1,0
       0     .12       0    87.7    .045       0   111.3     .12       0
  268.44      .1       0
#XS Ineff= 2 , 0
                          163.77         3404.95
Permanent Ineff=
       F       F
Bank Sta=87.7,111.3
XS Rating Curve= 0 ,0
Exp/Cntr(USF)=0,0
Exp/Cntr=0.3,0.1

Type RM Length L Ch R = 1 ,1457    ,226.5,227.7,225.2
XS GIS Cut Line= 2
2349815.77782136594493.9827397232349783.97548072594754.925021897
#Sta/Elev= 30
       0 3424.24    11.3  3420.9    19.3 3419.61    27.4 3416.38    39.5 3414.28
    51.6  3410.6    67.7  3403.3    71.7 3401.75    79.8 3398.06    81.5 3397.56
    87.8 3396.43    99.5 3395.13     108 3393.59     112 3393.54     121 3394.57
   128.1 3395.03   142.6 3394.92   153.4 3395.39   168.4 3395.14   171.3 3394.89
   176.5  3394.2   182.13394.912   192.9 3396.63   200.7 3398.47   204.7 3400.34
   214.4 3406.92   220.8 3410.87   236.9 3419.49   257.5 3427.66   262.9 3429.38
#Mann= 4 ,-1,0
       0      .1       0      10     .12       0   171.3    .045       0
   182.1     .12       0
Bank Sta=171.3,182.1
XS Rating Curve= 0 ,0
Exp/Cntr(USF)=0,0
Exp/Cntr=0.3,0.1

Type RM Length L Ch R = 1 ,1229    ,103.5,102.9,100
XS GIS Cut Line= 3
2349647.50628108594444.5607642772349621.42964318594648.945223443
2349654.55402105594739.156295075
#Sta/Elev= 30
       0  3434.3    12.7  3429.8    20.8 3427.43    40.9  3420.2      53  3414.9
    65.1 3410.73    73.2 3406.93    81.3  3405.3    89.3 3401.42    93.4 3400.39
    97.4 3398.72   105.5 3392.98   109.5 3391.03   113.5 3390.34   130.63389.401
   145.8 3388.82   151.13389.303   161.9 3390.98     174 3390.83   185.9 3390.23
   194.2 3390.94   198.2 3391.54   223.3 3396.93   245.8  3403.4   253.2 3405.85
   261.3 3409.68     272 3413.85   286.3 3419.15   295.8 3421.96   302.1 3424.65
#Mann= 5 ,-1,0
       0     .12       0   130.6    .045       0   151.1     .12       0
  266.04      .1       0  302.14     .12       0
Bank Sta=130.6,151.1
XS Rating Curve= 0 ,0
Exp/Cntr(USF)=0,0
Exp/Cntr=0.3,0.1

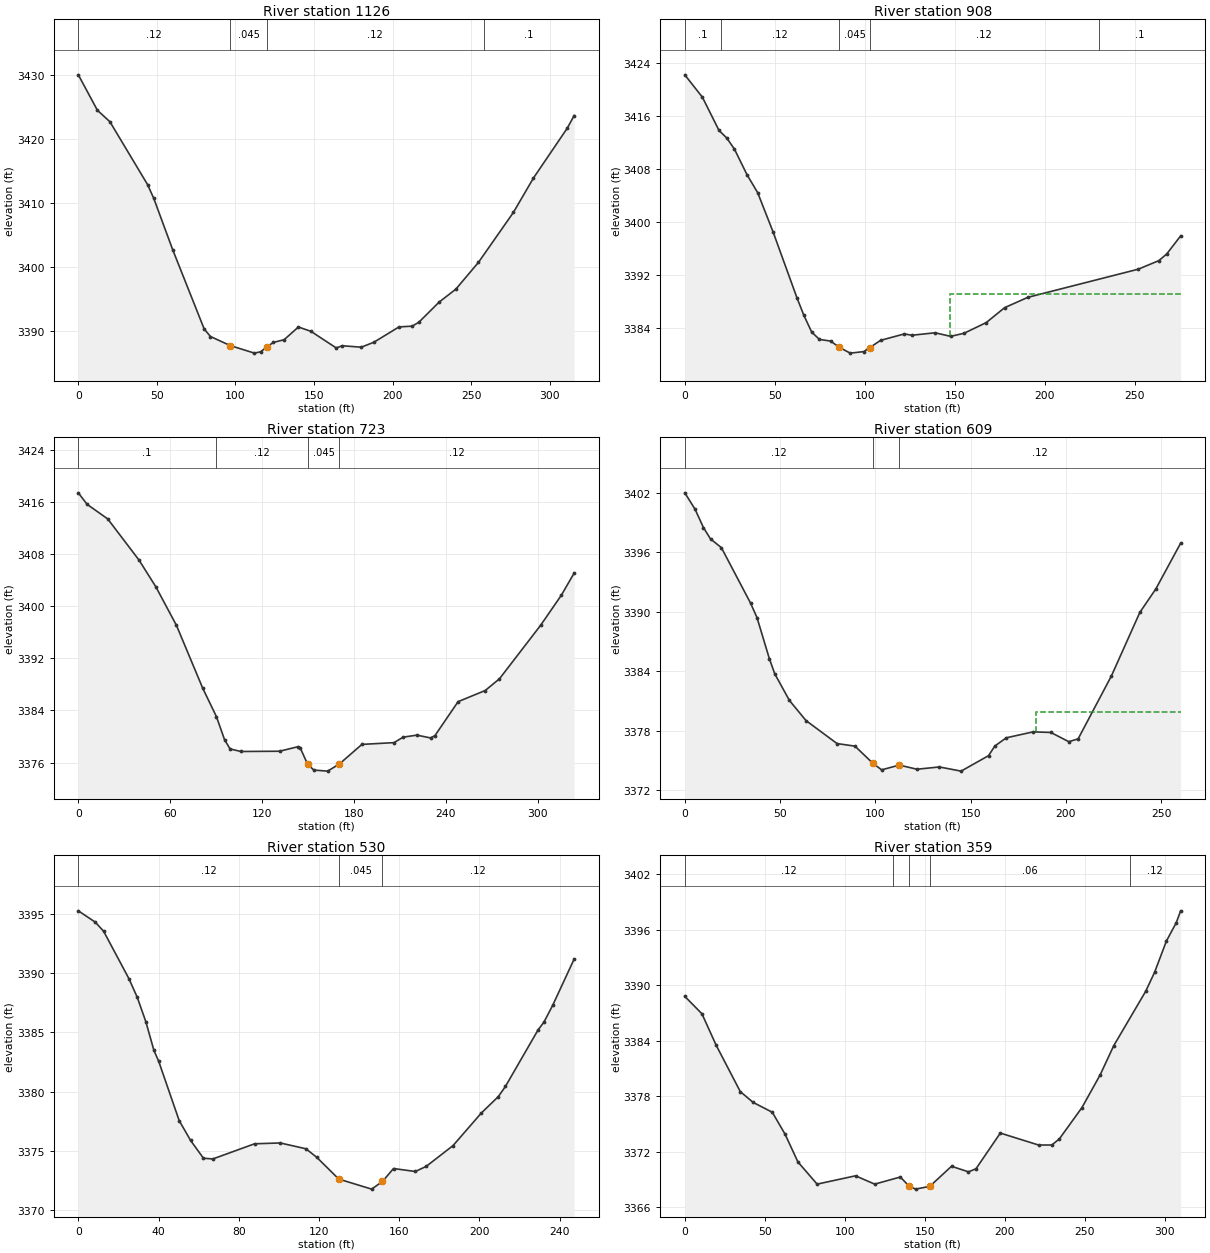
Type RM Length L Ch R = 1 ,1126    ,221.4,218.4,212.3
XS GIS Cut Line= 3
2349535.26486803594445.0560618162349538.52664655594652.994442923
2349577.66798888594753.294132633
#Sta/Elev= 30
       0 3430.09    12.1 3424.56    20.1 3422.75    44.1 3412.91      48 3410.77
    60.1 3402.71    80.1 3390.34    84.1 3389.16    96.7 3387.74   112.1 3386.56
   116.1 3386.78   120.1 3387.56   124.1 3388.23     131 3388.66   140.1 3390.65
   148.1 3389.96   164.1 3387.38   168.1 3387.71   180.1 3387.49   188.1 3388.26
   204.1 3390.66   212.5 3390.78   216.7 3391.38   229.6 3394.53   240.3 3396.57
   254.7 3400.76   276.9 3408.56   289.7 3413.95   311.2 3421.74   315.6 3423.72
#Mann= 4 ,-1,0
       0     .12       0    96.7    .045       0   120.1     .12       0
  257.96      .1       0
Bank Sta=96.7,120.1
XS Rating Curve= 0 ,0
Exp/Cntr(USF)=0,0
Exp/Cntr=0.3,0.1

Type RM Length L Ch R = 1 ,908     ,184.2,185.3,182.5
XS GIS Cut Line= 2
2349297.15503554594487.4591826692349396.63928062594744.324241683
#Sta/Elev= 30
       0 3422.24     9.8 3418.85      19 3413.85    23.3 3412.71    27.6 3411.02
    34.6 3407.15    40.5 3404.45      49 3398.57    62.4 3388.53    66.2 3385.92
    70.5 3383.42    74.8 3382.31      81 3382.06    85.9 3381.11    91.9 3380.24
    99.5 3380.47   102.7 3381.06   108.8 3382.17     122 3383.14   126.2 3382.94
   139.1 3383.31   147.7 3382.77   155.2 3383.24   167.5 3384.85   177.7  3387.1
   190.6 3388.66     252 3392.91   263.4  3394.2   267.8 3395.21   275.5 3397.93
#Mann= 5 ,-1,0
       0      .1       0      20     .12       0    85.9    .045       0
   102.7     .12       0     230      .1       0
#XS Ineff= 2 , 0
                          147.51         3389.15
Permanent Ineff=
       F       F
Bank Sta=85.9,102.7
XS Rating Curve= 0 ,0
Exp/Cntr(USF)=0,0
Exp/Cntr=0.3,0.1

Type RM Length L Ch R = 1 ,723     ,113.6,114.2,113
XS GIS Cut Line= 2
2349112.04910413594520.0769679412349258.82913785594808.744367595
#Sta/Elev= 30
       0 3417.37     5.7 3415.61    19.2 3413.37    39.6 3407.07    50.6 3402.97
    64.1 3397.04    81.2 3387.43    90.2 3383.05    95.5 3379.51    99.1  3378.1
   106.2 3377.71   131.4 3377.75   143.7 3378.46   144.8 3378.32   149.7 3375.77
   153.8 3374.86   162.8  3374.7   170.5  3375.8   185.2  3378.8   206.2 3379.07
   212.1 3379.91   221.1 3380.22     230 3379.79   232.9 3380.15     248 3385.35
   265.7 3387.06     275 3388.85   301.9 3397.06   315.4 3401.66   323.8 3405.07
#Mann= 4 ,-1,0
       0      .1       0      90     .12       0   149.7    .045       0
   170.5     .12       0
Bank Sta=149.7,170.5
XS Rating Curve= 0 ,0
Exp/Cntr(USF)=0,0
Exp/Cntr=0.3,0.1

Type RM Length L Ch R = 1 ,609     ,77.9,78.2,76
XS GIS Cut Line= 2
2349025.19084162594608.7731056072349159.80267507594831.481688699
#Sta/Elev= 30
       0 3402.01     5.4 3400.35     9.8  3398.5    13.5 3397.36    19.2 3396.48
    34.5 3390.89    37.9 3389.42    44.4 3385.27    47.2 3383.76    54.9 3381.07
    63.6 3379.04    79.9 3376.72    89.3 3376.46    98.7 3374.73   103.3 3374.07
   112.6 3374.55   121.8 3374.13   133.6 3374.36     145 3373.94   159.4  3375.5
   162.7 3376.47   168.7  3377.3   182.8  3377.9   192.1 3377.84   201.5 3376.91
   206.4 3377.19   223.9 3383.55   238.8 3389.95   247.2 3392.32   260.2 3396.93
#Mann= 3 ,-1,0
       0     .12       0    98.7    .045       0   112.6     .12       0
#XS Ineff= 2 , 0
                          184.56         3379.89
Permanent Ineff=
       F       F
Bank Sta=98.7,112.6
XS Rating Curve= 0 ,0
Exp/Cntr(USF)=0,0
Exp/Cntr=0.3,0.1

Type RM Length L Ch R = 1 ,530     ,158.5,170.9,179.5
XS GIS Cut Line= 3
2348989.94297489594637.1762968592349023.62899263594744.178941443
2349115.43990372594843.255464206
#Sta/Elev= 30
       0 3395.27     8.4 3394.32    12.6 3393.55    25.2 3389.55    29.4 3387.96
    33.7 3385.89    37.7 3383.48    40.1 3382.55    50.3 3377.55      56 3375.87
    62.4 3374.37    67.1 3374.31    87.9 3375.59   100.7 3375.66   113.5 3375.17
   118.9 3374.45   129.9 3372.61   146.3 3371.76   151.7 3372.41   157.2  3373.5
   168.1 3373.25   173.5 3373.68   186.9 3375.44     201 3378.19   209.5 3379.58
     213 3380.43   229.3 3385.21   232.2 3385.86   236.6 3387.29   247.3  3391.2
#Mann= 3 ,-1,0
       0     .12       0   129.9    .045       0   151.7     .12       0
Bank Sta=129.9,151.7
XS Rating Curve= 0 ,0
Exp/Cntr(USF)=0,0
Exp/Cntr=0.3,0.1

Type RM Length L Ch R = 1 ,359     ,45.3,44,43
XS GIS Cut Line= 3
2348896.98668633594666.5135641332348897.78287268594834.708124671
2348989.94297489594942.331986969
#Sta/Elev= 30
       0 3388.81    10.7 3386.93    19.6 3383.53    34.7 3378.51    42.7 3377.35
    54.7 3376.28    62.7  3373.9    70.7 3370.91    82.7 3368.51   106.7 3369.41
   118.7 3368.51   134.7 3369.28   140.1 3368.31   144.2 3367.97   153.1 3368.27
   166.7 3370.44   177.3 3369.84     182 3370.17   197.2 3374.03   221.1 3372.74
   229.4 3372.74   234.1  3373.4   248.2 3376.78   259.6 3380.32   268.1 3383.48
     288 3389.34   293.6  3391.4     301 3394.79   307.2 3396.79   309.9 3398.06
#Mann= 5 ,-1,0
       0     .12       0     130     .06       0   140.1    .045       0
   153.1     .06       0   278.2     .12       0
Bank Sta=140.1,153.1
XS Rating Curve= 0 ,0
Exp/Cntr(USF)=0,0
Exp/Cntr=0.3,0.1