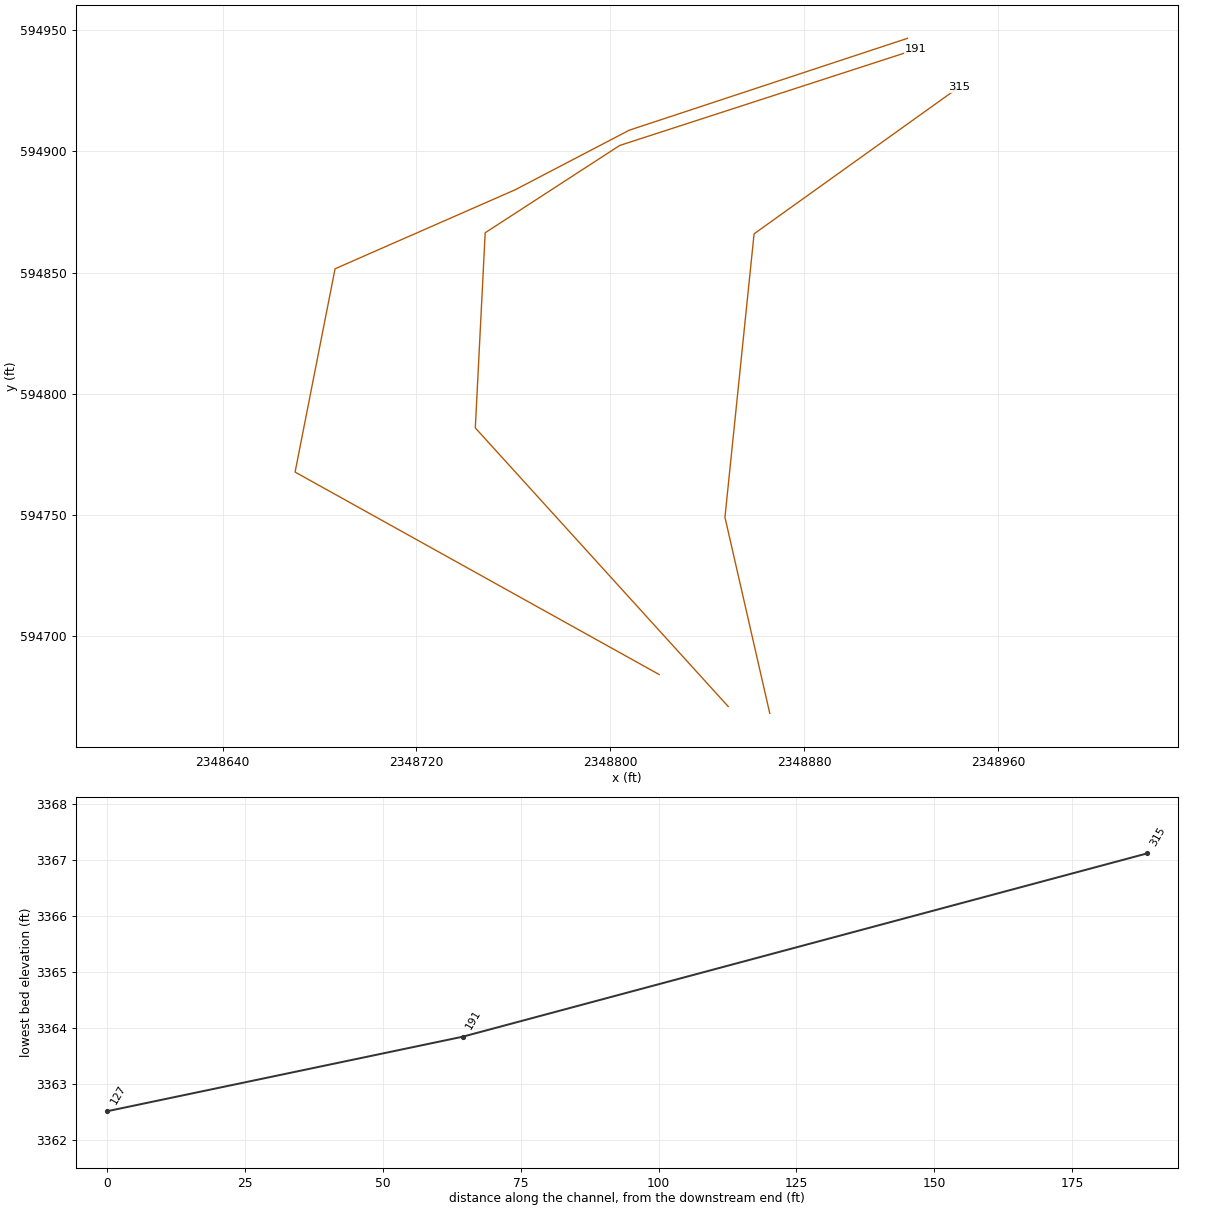
HEC-RAS study BRNGRN.prj: BRNGRN

--- BRNGRN.g01 (geometry) --- (continued)

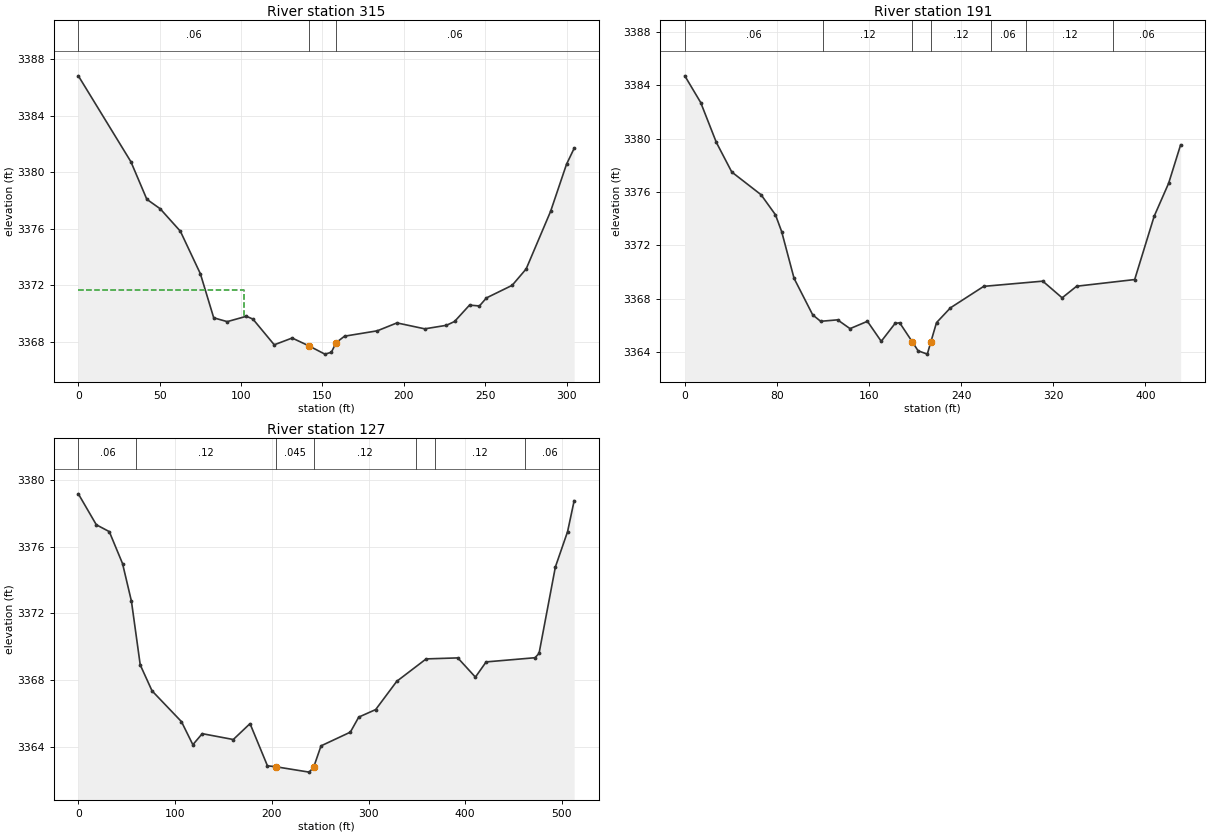
Type RM Length L Ch R = 1 ,315     ,117.7,124.1,120.8
XS GIS Cut Line= 4
2348865.80697742 594668.102742622348847.31088864594749.023131035
2348859.33334634594866.0108925722348943.95295251594926.585583329
#Sta/Elev= 30
       0 3386.81    32.3 3380.73    42.1 3378.07    50.3  3377.4    62.7 3375.81
      75  3372.8    83.2 3369.68    91.5 3369.41   103.3 3369.79   107.3 3369.59
   120.4 3367.77   131.4 3368.25     1423367.677   151.5 3367.11   155.5 3367.24
   158.4 3367.92   163.6 3368.38   183.7 3368.76   195.8 3369.32   212.9  3368.9
   226.2 3369.15   231.2 3369.42   240.4 3370.58   246.5 3370.52   250.8 3371.09
   266.6 3371.98   275.2 3373.14   290.2 3377.21     300 3380.55   304.7 3381.68
#Mann= 3 ,-1,0
       0     .06       0     142    .045       0   158.4     .06       0
#XS Ineff= 2 , 0
          101.94 3371.63
Permanent Ineff=
       F       F
Bank Sta=142,158.4
XS Rating Curve= 0 ,0
Exp/Cntr(USF)=0,0
Exp/Cntr=0.3,0.1

Type RM Length L Ch R = 1 ,191     ,77.5,64.5,63.6
XS GIS Cut Line= 5
2348848.66048806594670.9342248222348744.28357519594785.911917905
2348748.36079835594866.4515331392348803.88645784594902.483629971
2348926.12941205594942.136281389
#Sta/Elev= 30
       0  3384.7    13.8  3382.7    27.4 3379.71    40.8 3377.49    66.2 3375.79
    78.7 3374.29    84.1 3373.03    94.9 3369.52   111.1 3366.78     118  3366.3
   132.7 3366.41   143.5 3365.75   158.6  3366.3   170.6  3364.8   182.6 3366.14
   186.6 3366.19   197.63364.759   202.6 3364.09   210.6 3363.84   213.6 3364.73
   218.6  3366.2   230.7 3367.31   259.6 3368.92   310.9 3369.31   327.7 3368.06
   340.3 3368.93   390.7 3369.43   407.6 3374.17   420.2 3376.65   430.6 3379.53
#Mann= 7 ,-1,0
       0     .06       0     120     .12       0   197.6    .045       0
   213.6     .12       0  265.93     .06       0  295.93     .12       0
  372.12     .06       0
Bank Sta=197.6,213.6
XS Rating Curve= 0 ,0
Exp/Cntr(USF)=0,0
Exp/Cntr=0.3,0.1

Type RM Length L Ch R = 1 ,127     ,,,
XS GIS Cut Line= 6
2348820.14290692594684.1480353442348669.90541578594767.691313127
2348686.40345803594851.5856130852348760.82015925594884.230675412
2348807.78437702594908.7671444612348922.61866601594946.690475802
#Sta/Elev= 30
       0 3379.15    18.6  3377.3      32 3376.89    45.7 3374.98    54.9 3372.73
      64 3368.92    76.2 3367.37   106.6 3365.53   118.4 3364.15   128.1 3364.81
   160.2 3364.46   177.5 3365.41   195.5 3362.89   204.4 3362.83   238.6 3362.51
   243.2 3362.79   250.9 3364.08   281.2  3364.9   289.9  3365.8   307.4 3366.25
   329.2 3367.94   359.6 3369.28   392.3 3369.34   410.5 3368.19   421.6  3369.1
   472.1 3369.35   476.3 3369.61   493.2 3374.78   505.8 3376.89   512.6 3378.74
#Mann= 7 ,-1,0
       0     .06       0      60     .12       0   204.4    .045       0
   243.2     .12       0  348.67     .06       0  368.67     .12       0
  461.65     .06       0
Bank Sta=204.4,243.2
XS Rating Curve= 0 ,0
Exp/Cntr(USF)=0,0
Exp/Cntr=0.3,0.1
LCMann Table=0

Chan Stop Cuts=-1
Use User Specified Reach Order=0
Composite Channel Slope=5